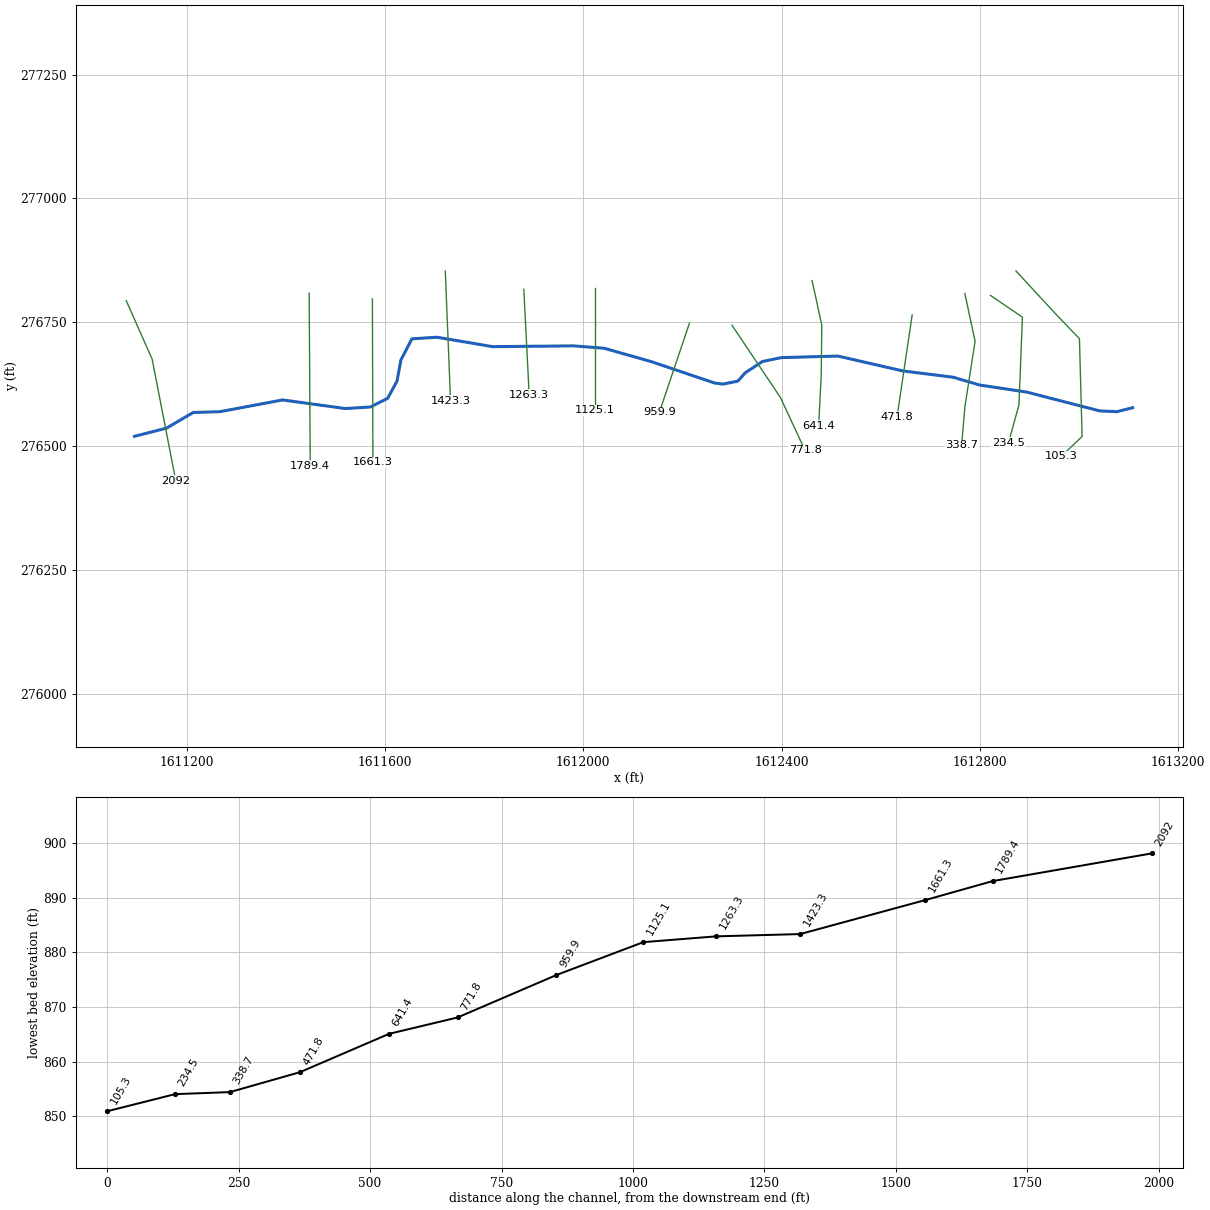
--- NP7.prj (project) ---

Proj Title=NP7
Current Plan=p01
Default Exp/Contr=0,0
English Units
Geom File=g01
Flow File=f01
Plan File=p01
BEGIN DESCRIPTION:
END DESCRIPTION:
DSS Export Rating Curves= 0
DSS Export Rating Curve Sorted= 0
DSS Export Volume Flow Curves= 0
DXF OffsetX= 0
DXF OffsetY= 0
DXF ScaleX= 0
DXF ScaleY= 0

--- NP7.p01 (plan) ---

Plan Title=Floodplain
Program Version=4.00
Geom File=g01
Flow File=f01
K Sum by GR=0
Std Step Tol=0.01
Critical Tol=0.01
Num of Std Step Trials=20
Max Error Tol=0.3
Flow Tol Ratio=0.001
Split Flow NTrial=30
Split Flow Tol=0.02
Split Flow Ratio=0.02
Log Output Level=0
Friction Slope Method=1
Unsteady Friction Slope Method=2
Unsteady Bridges Friction Slope Method=1
Global Log Level=0
CheckData=False
Run HTab=0
Run UNet=0
Run PostProcess=0
UNET Theta=0
UNET Theta Warmup=0
UNET ZTol=0
UNET ZSATol=0
UNET MxIter=0
UNET MaxInSteps=0
UNET DtIC=0
UNET DtMin=0
UNET MaxCRTS=0
UNET WFStab=0
UNET SFStab=0
UNET WFX=0
UNET SFX=0
UNET DSS MLevel=0
UNET DZMax Abort=0
UNET Convert EG Bridges=0
UNET Use Existing IB Tables=0
UNET Froude Limit=0
UNET Froude Power=0
Write IC File=0
Echo Input=False
Echo Output=False
Write Detailed=0

--- NP7.f01 (steady flow) ---

Flow Title=NFF Regression Equation
Program Version=4.10
Number of Profiles= 1
Profile Names=P100yr
River Rch & RM=NP7,Main            ,2092
335.2524
River Rch & RM=NP7,Main            ,771.8
367.8503
River Rch & RM=NP7,Main            ,471.8
373.2522
Boundary for River Rch & Prof#=NP7,Main            , 1
Up Type= 0
Dn Type= 3
Dn Slope=0.02418
DSS Import GetInterval= 0
DSS Import GetPeak= 0
DSS Import FillOption= 0

--- NP7.g01 (geometry) ---

Geom Title=USGS 10m DEM
Program Version=4.10

River Reach=NP7             ,Main
Reach XY= 30
     1611094.673      276519.822     1611159.319      276536.301
     1611213.097      276567.935     1611266.875      276569.516
     1611393.411      276593.242      1611519.79      276575.843
     1611570.404      276579.007     1611605.202      276596.405
     1611624.182      276631.203     1611632.091      276673.909
     1611654.235      276716.615     1611704.849      276719.779
     1611817.151      276700.798     1611980.066       276702.38
     1612041.753      276697.635     1612136.655      276670.746
     1612264.541      276627.452     1612281.693      276625.223
     1612311.923      276631.246     1612326.507      276647.913
     1612361.258      276670.746     1612399.219      276678.654
     1612513.418      276681.818     1612644.699      276651.765
     1612745.929      276639.112     1612799.707      276623.294
     1612894.609      276609.059     1613041.708      276571.098
     1613076.506      276569.516     1613108.289      276577.521

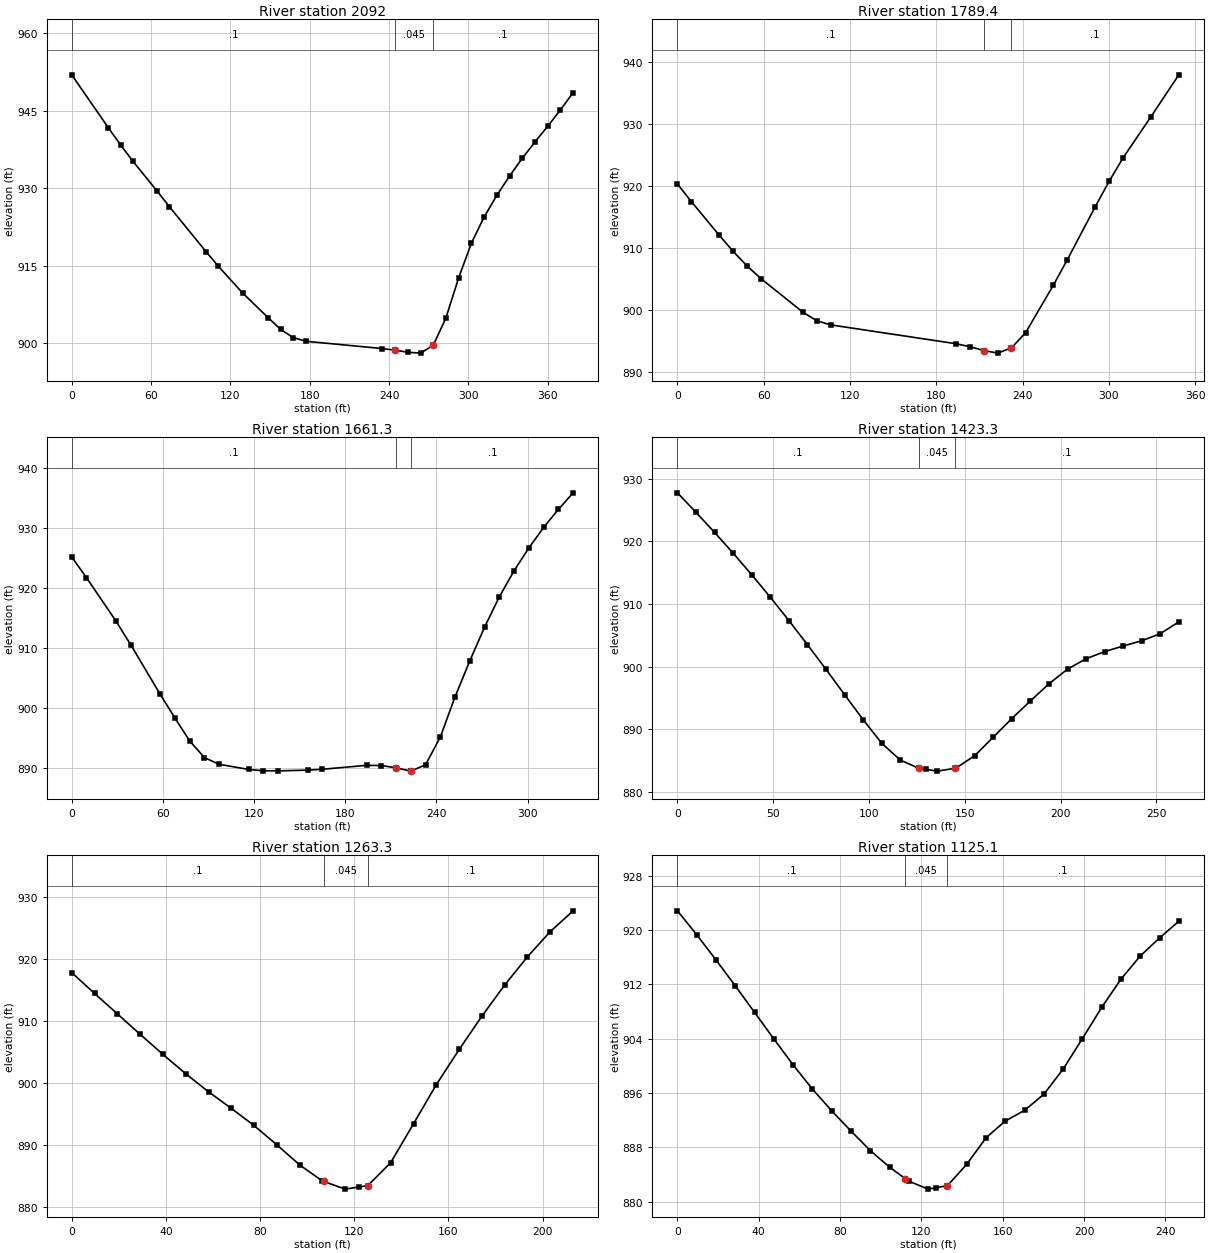
Type RM Length L Ch R = 1 ,2092    ,306.7,302.6,298
XS GIS Cut Line= 3
     1611077.952      276793.639     1611130.226      276675.488
     1611177.876      276430.086
#Sta/Elev= 29
       0  951.95    27.7   941.7    36.9   938.4    46.1  935.28    64.6  929.44
    73.8  926.45   101.5  917.75   110.7  914.95   129.2  909.74   148.4  904.98
     158  902.69   167.7  901.06   177.3  900.38     235  898.97   244.6  898.66
   254.2  898.26   263.8  898.09   273.4  899.61     283   904.9   292.6  912.64
   302.3   919.4   311.9  924.43   321.5  928.62   331.1  932.36   340.7  935.78
   350.3  938.95     360     942   369.6  945.16   379.2  948.52
#Mann= 3 , 0 , 0
       0      .1       0   244.6    .045       0   273.4      .1       0
Bank Sta=244.6,273.4
XS Rating Curve= 0 ,0
Exp/Cntr=0.3,0.1

Type RM Length L Ch R = 1 ,1789.4  ,128.9,128.1,127.6
XS GIS Cut Line= 2
     1611447.001      276808.785     1611449.127      276460.115
#Sta/Elev= 23
       0   920.3     9.7  917.46    29.1  912.03    38.7  909.44    48.4  907.09
    58.1  905.04    87.2  899.63    96.8  898.26   106.5  897.58   193.7  894.54
   203.4  894.06   213.1  893.44   222.8  893.02   231.7  893.83   232.4  893.89
   242.1  896.31   261.5  904.01   271.2  908.12   290.6  916.66   300.2  920.73
   309.9  924.52   329.3  931.16   348.7  937.92
#Mann= 3 , 0 , 0
       0      .1       0   213.1    .045       0   231.7      .1       0
Bank Sta=213.1,231.7
XS Rating Curve= 0 ,0
Exp/Cntr=0.3,0.1

Type RM Length L Ch R = 1 ,1661.3  ,237.6,238,237.7
XS GIS Cut Line= 2
      1611574.51      276797.392     1611575.595      276467.531
#Sta/Elev= 30
       0  925.19     9.7  921.74    29.1  914.52    38.8  910.59    58.2  902.33
    67.9  898.38    77.6  894.58    87.3   891.8      97  890.69   116.4  889.83
   126.1  889.61   135.8  889.59   155.2  889.72   164.9  889.86     194  890.51
   203.7  890.48   213.4   890.1   223.1  889.55   223.5  889.59   232.8  890.61
   242.6  895.27   252.2  901.92     262  907.94   271.6  913.49   281.4  918.58
   291.1  922.92   300.8   926.7   310.5   930.1   320.2   933.1   329.9  935.86
#Mann= 3 , 0 , 0
       0      .1       0   213.4    .045       0   223.5      .1       0
Bank Sta=213.4,223.5
XS Rating Curve= 0 ,0
Exp/Cntr=0.3,0.1

Type RM Length L Ch R = 1 ,1423.3  ,159.8,160,160.2
XS GIS Cut Line= 2
     1611721.552      276853.344     1611732.182      276591.841
#Sta/Elev= 30
       0  927.73     9.7  924.61    19.4  921.41    29.1  918.09    38.8  914.65
    48.5  911.06    58.2  907.34    67.8  903.52    77.6  899.55    87.2  895.54
    96.9  891.55   106.6  887.78   116.3   885.1     126  883.78   129.9   883.6
   135.7  883.33   144.9  883.79   145.4  883.82   155.1  885.78   164.8  888.74
   174.5  891.71   184.2  894.52   193.9  897.26   203.6   899.6   213.2  901.25
     223   902.4   232.6  903.29   242.3  904.12     252  905.26   261.7  907.14
#Mann= 3 , 0 , 0
       0      .1       0     126    .045       0   144.9      .1       0
Bank Sta=126,144.9
XS Rating Curve= 0 ,0
Exp/Cntr=0.3,0.1

Type RM Length L Ch R = 1 ,1263.3  ,139.4,138.3,137.1
XS GIS Cut Line= 2
     1611879.957      276816.706     1611890.808      276604.033
#Sta/Elev= 25
       0  917.81     9.7  914.44    19.4  911.15      29  907.88    38.7  904.64
    48.4  901.51    58.1   898.6    67.8  895.92    77.4  893.17    87.1  890.06
    96.8  886.82   106.5  884.22     107  884.15   116.2  882.91     122  883.26
   125.8  883.49   135.5  887.18   145.2  893.45   154.9  899.76   164.6  905.42
   174.2  910.77   183.9  915.79   193.6  920.36   203.3  924.42     213  927.76
#Mann= 3 , 0 , 0
       0      .1       0     107    .045       0   125.8      .1       0
Bank Sta=107,125.8
XS Rating Curve= 0 ,0
Exp/Cntr=0.3,0.1

Type RM Length L Ch R = 1 ,1125.1  ,172.5,165.2,157.8
XS GIS Cut Line= 2
     1612023.935      276818.551     1612023.935       276571.93
#Sta/Elev= 29
       0  922.84     9.5  919.31      19  915.59    28.5  911.77    37.9   907.9
    47.4  903.98    56.9  900.14    66.4  896.58    75.9  893.37    85.4  890.39
    94.9  887.52   104.3  885.09     112  883.41   113.8  883.02   123.3  881.85
     127  882.05   132.8  882.36   142.3  885.52   151.8  889.42   161.2  891.87
   170.7  893.45   180.2  895.82   189.7  899.53   199.2  904.03   208.7  908.64
   218.2   912.8   227.6  916.18   237.1  918.85   246.6   921.3
#Mann= 3 , 0 , 0
       0      .1       0     112    .045       0   132.8      .1       0
Bank Sta=112,132.8
XS Rating Curve= 0 ,0
Exp/Cntr=0.3,0.1

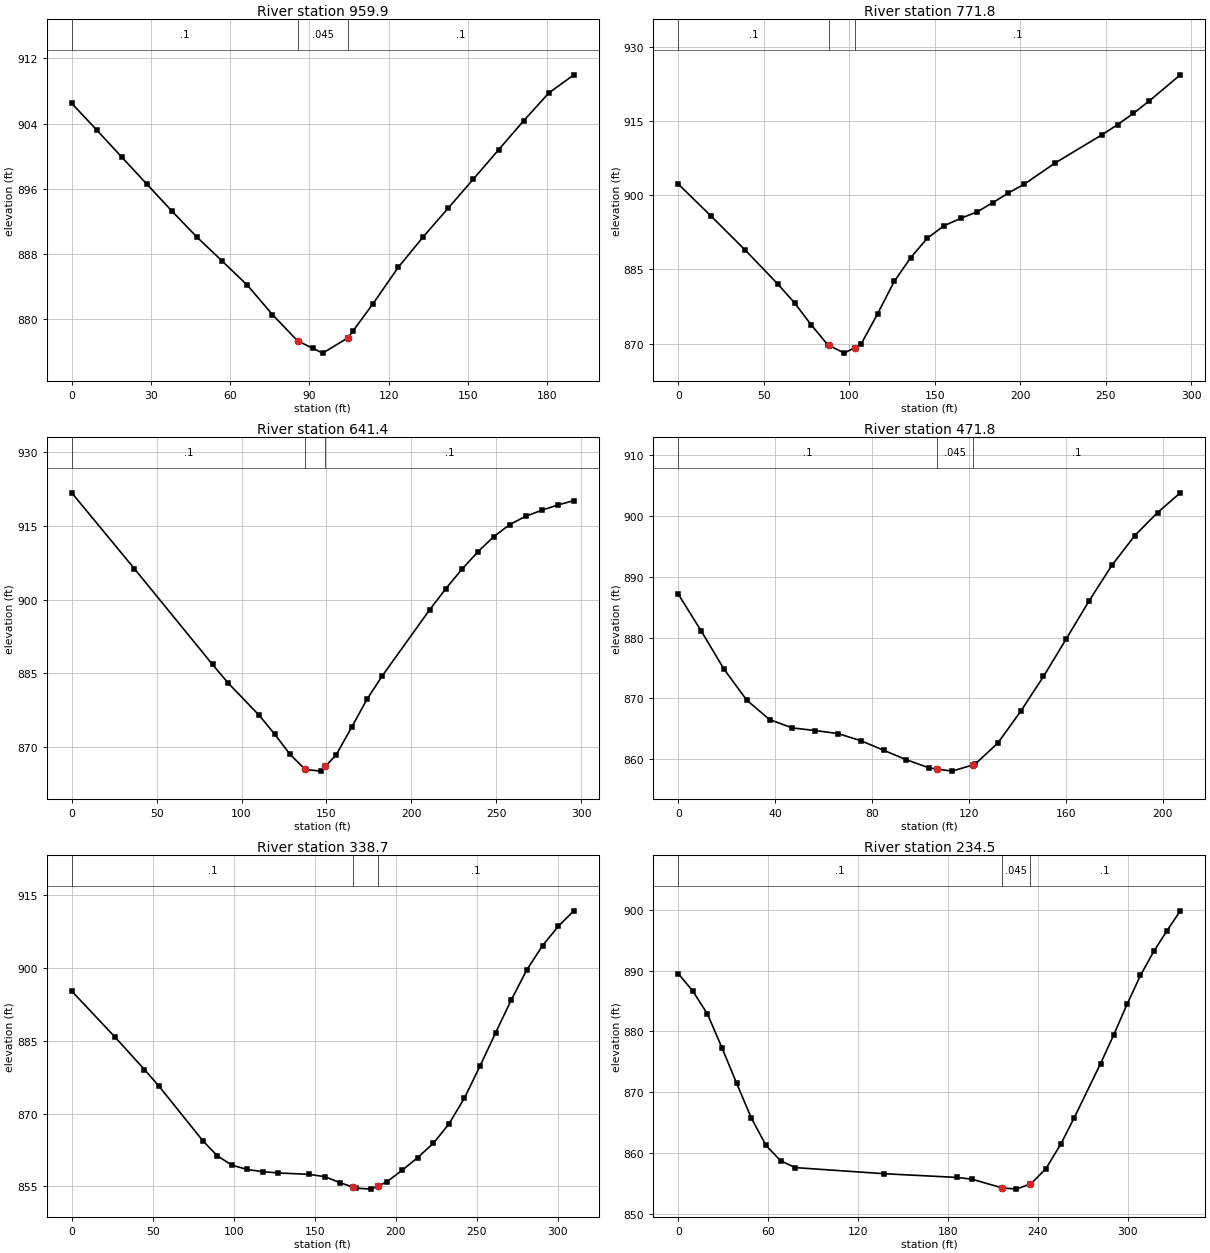
Type RM Length L Ch R = 1 ,959.9   ,166.9,188.1,209.3
XS GIS Cut Line= 2
     1612214.158      276748.347     1612153.395      276568.225
#Sta/Elev= 23
       0  906.49     9.5   903.2      19  899.87    28.5  896.55      38  893.24
    47.5  890.04      57  887.12    66.5  884.17      76  880.56    85.5  877.34
    91.4  876.41      95  875.84   104.6  877.73   106.4  878.52   114.1  881.92
   123.6  886.36   133.1  890.12   142.6  893.66   152.1  897.21   161.6  900.79
   171.1  904.35   180.6  907.76   190.1  909.99
#Mann= 3 , 0 , 0
       0      .1       0    85.5    .045       0   104.6      .1       0
Bank Sta=85.5,104.6
XS Rating Curve= 0 ,0
Exp/Cntr=0.3,0.1

Type RM Length L Ch R = 1 ,771.8   ,143.8,130.4,116.5
XS GIS Cut Line= 3
     1612299.879      276744.007     1612397.311      276598.814
     1612447.448      276491.186
#Sta/Elev= 27
       0   902.3    19.4  895.73    38.9  889.02    58.3  882.02      68  878.25
    77.7  873.81    87.4  869.77    88.2  869.63    97.1  868.07   103.2   869.2
   106.9  869.88   116.6  876.05   126.3  882.57     136  887.42   145.7  891.34
   155.4  893.84   165.1  895.34   174.8  896.66     184  898.53   193.1  900.49
   202.2  902.23   220.5  906.57   247.9  912.28     257  914.33   266.2   916.6
   275.3  919.06   293.6  924.39
#Mann= 3 , 0 , 0
       0      .1       0    88.2    .045       0   103.2      .1       0
Bank Sta=88.2,103.2
XS Rating Curve= 0 ,0
Exp/Cntr=0.3,0.1

Type RM Length L Ch R = 1 ,641.4   ,172.7,169.6,166.6
XS GIS Cut Line= 4
     1612461.554      276834.067     1612481.086      276744.007
        1612480.       276644.18     1612474.761       276540.64
#Sta/Elev= 24
       0  921.73    36.9  906.27    82.9  886.78    92.2  882.97   110.3  876.46
   119.4  872.64   128.5  868.51   137.5  865.41   146.6  865.07  149.38  866.06
   155.7  868.36   164.8  873.98   173.8  879.66   182.9  884.48   210.8  897.93
   220.3  902.21   229.7  906.14   239.1   909.7   248.5   912.8     258  915.28
   267.4  916.97   276.8  918.18   286.2  919.25   295.7  920.15
#Mann= 3 , 0 , 0
       0      .1       0   137.5    .045       0  149.38      .1       0
Bank Sta=137.5,149.38
XS Rating Curve= 0 ,0
Exp/Cntr=0.3,0.1

Type RM Length L Ch R = 1 ,471.8   ,133.3,133.1,132.9
XS GIS Cut Line= 2
     1612663.377      276764.623     1612632.995      276559.545
#Sta/Elev= 25
       0  887.14     9.4  881.14    18.8  874.86    28.3  869.71    37.7  866.52
    47.1  865.15    56.5  864.72      66  864.22    75.4  863.05    84.8  861.48
    94.2  859.92   103.7  858.57   106.8   858.4   113.1  858.05   121.8  859.09
   122.5  859.17   131.9  862.64   141.4  867.88   150.8   873.6   160.2  879.78
   169.6     886     179  891.84   188.5  896.75   197.9  900.54   207.3  903.78
#Mann= 3 , 0 , 0
       0      .1       0   106.8    .045       0   121.8      .1       0
Bank Sta=106.8,121.8
XS Rating Curve= 0 ,0
Exp/Cntr=0.3,0.1

Type RM Length L Ch R = 1 ,338.7   ,101.6,104.2,106.8
XS GIS Cut Line= 4
     1612769.714      276808.026      1612790.33      276711.455
     1612769.714      276579.076     1612763.204      276502.036
#Sta/Elev= 30
       0  895.22    26.9  885.68    44.9  879.05    53.9  875.61    80.8  864.43
    89.8   861.3    98.8  859.36   108.3  858.46   117.9     858   127.5  857.75
   146.6  857.45   156.2  856.98   165.7  855.74   173.9  854.78   175.3  854.62
   184.9  854.41   188.9  855.03   194.4  855.88     204   858.3   213.6  860.92
   223.2  863.84   232.7  867.76   242.4  873.16     252  879.74   261.7  886.65
   271.4  893.44     281  899.64   290.7  904.62   300.4  908.59     310  911.78
#Mann= 3 , 0 , 0
       0      .1       0   173.9    .045       0   188.9      .1       0
Bank Sta=173.9,188.9
XS Rating Curve= 0 ,0
Exp/Cntr=0.3,0.1

Type RM Length L Ch R = 1 ,234.5   ,127.4,129.1,130.8
XS GIS Cut Line= 4
     1612821.306      276804.269     1612885.816      276760.283
      1612878.85      276583.349     1612857.605      276506.376
#Sta/Elev= 26
       0  889.51     9.8  886.59    19.5  882.86    29.3  877.22      39  871.44
    48.8  865.72    58.6  861.22    68.3  858.71    78.1  857.58   137.1  856.58
   186.3  855.96   196.1  855.67   215.8  854.26   225.6  854.04   234.7  854.87
   235.5  854.94   245.3  857.41   255.2  861.42     264  865.68   281.8   874.7
   290.6  879.44   299.5  884.47   308.4  889.19   317.3  893.16   326.1  896.56
     335  899.83
#Mann= 3 , 0 , 0
       0      .1       0   215.8    .045       0   234.7      .1       0
Bank Sta=215.8,234.7
XS Rating Curve= 0 ,0
Exp/Cntr=0.3,0.1

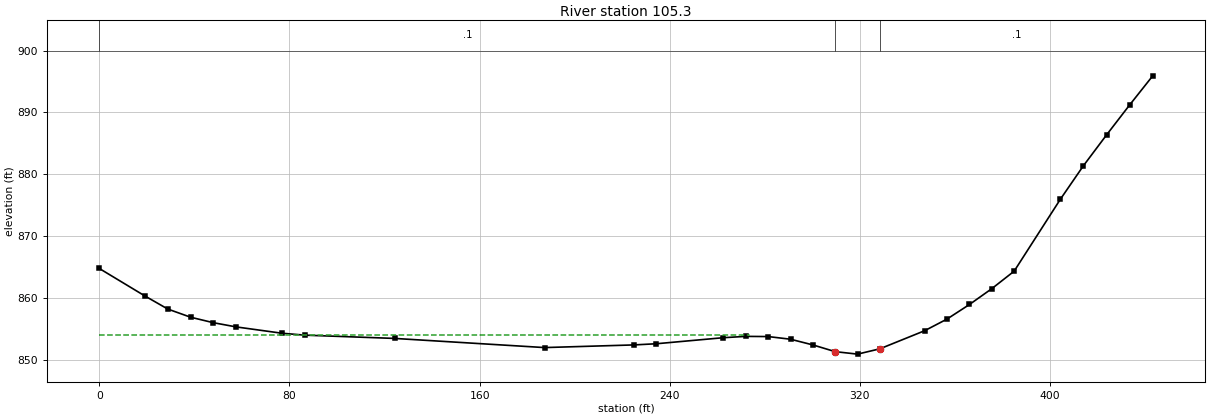
Type RM Length L Ch R = 1 ,105.3   ,100.6,105.3,110.2
XS GIS Cut Line= 5
     1612872.796      276853.599     1612950.921      276768.963
     1613000.834       276716.88     1613006.259      276519.397
     1612963.941       276479.25
#Sta/Elev= 30
       0  864.76    19.2  860.31    28.8   858.2    38.4  856.88      48  855.99
    57.6  855.31    76.8  854.29    86.4  853.98   124.2  853.45   187.3  851.97
     225   852.4   234.4  852.59   262.6  853.57     272  853.78   281.4  853.75
   290.8  853.32   300.2   852.4   309.6  851.31     319  850.91   328.4  851.77
   347.2  854.69   356.6  856.57   366.1  858.94   375.5   861.5   384.9  864.33
   404.3  875.94     414  881.36   423.8  886.38   433.5  891.22   443.2  895.92
#Mann= 3 , 0 , 0
       0      .1       0   309.6    .045       0   328.4      .1       0
#XS Ineff= 2 , 0
          273.24  853.93
Permanent Ineff=
       F       F
Bank Sta=309.6,328.4
XS Rating Curve= 0 ,0
Exp/Cntr=0.3,0.1

Chan Stop Cuts=-1
Use User Specified Reach Order=0
Composite Channel Slope=5